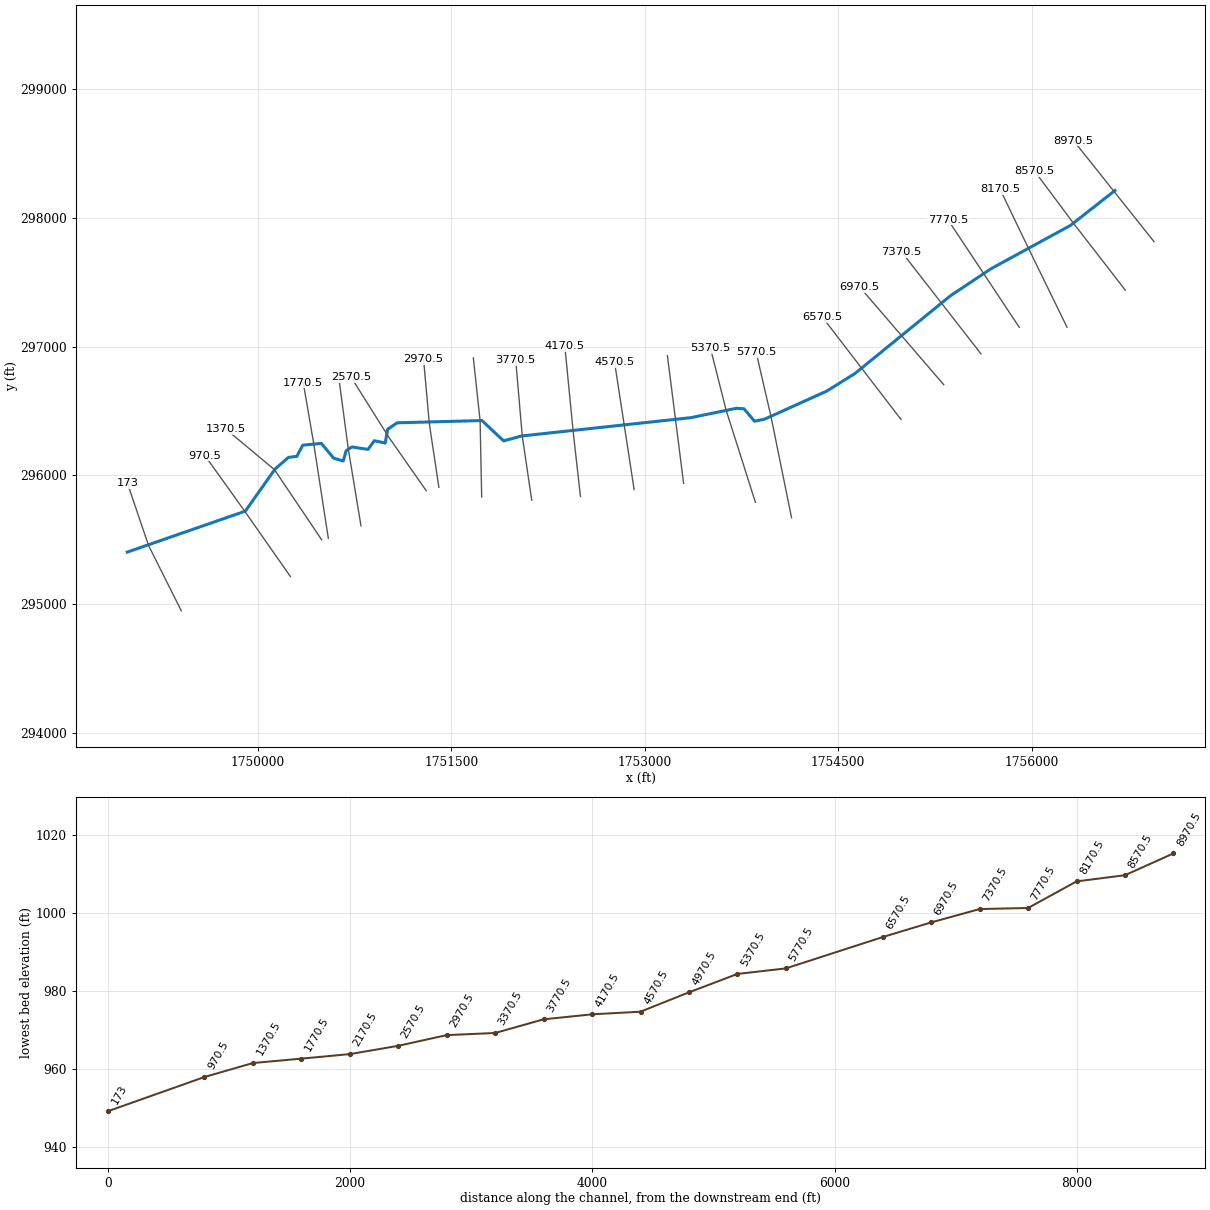
--- BarnetRn.prj (project) ---

Proj Title=BarnetRn
Current Plan=p01
Default Exp/Contr=0,0
English Units
Geom File=g01
Flow File=f01
Plan File=p01
BEGIN DESCRIPTION:
END DESCRIPTION:
DSS Export Rating Curves= 0
DSS Export Rating Curve Sorted= 0
DSS Export Volume Flow Curves= 0
DXF OffsetX= 0
DXF OffsetY= 0
DXF ScaleX= 0
DXF ScaleY= 0

--- BarnetRn.p01 (plan) ---

Plan Title=Floodplain
Program Version=4.00
Geom File=g01
Flow File=f01
K Sum by GR=0
Std Step Tol=0.01
Critical Tol=0.01
Num of Std Step Trials=20
Max Error Tol=0.3
Flow Tol Ratio=0.001
Split Flow NTrial=30
Split Flow Tol=0.02
Split Flow Ratio=0.02
Log Output Level=0
Friction Slope Method=1
Unsteady Friction Slope Method=2
Unsteady Bridges Friction Slope Method=1
Global Log Level=0
CheckData=False
Run HTab=0
Run UNet=0
Run PostProcess=0
UNET Theta=0
UNET Theta Warmup=0
UNET ZTol=0
UNET ZSATol=0
UNET MxIter=0
UNET MaxInSteps=0
UNET DtIC=0
UNET DtMin=0
UNET MaxCRTS=0
UNET WFStab=0
UNET SFStab=0
UNET WFX=0
UNET SFX=0
UNET DSS MLevel=0
UNET DZMax Abort=0
UNET Convert EG Bridges=0
UNET Use Existing IB Tables=0
UNET Froude Limit=0
UNET Froude Power=0
Write IC File=0
Echo Input=False
Echo Output=False
Write Detailed=0

--- BarnetRn.f01 (steady flow) ---

Flow Title=NFF Regression Equation
Program Version=4.00
Number of Profiles=1
Profile Names=P100yr
River Rch & RM=BarnetRn,Main      ,8970.5
726.2800
River Rch & RM=BarnetRn,Main      ,7770.5
792.5736
River Rch & RM=BarnetRn,Main      ,4570.5
870.4608
River Rch & RM=BarnetRn,Main      ,4570.5
1165.694
River Rch & RM=BarnetRn,Main      ,3370.5
1178.014
River Rch & RM=BarnetRn,Main      ,3370.5
1400.268
River Rch & RM=BarnetRn,Main      ,173
1440.775
Boundary for River Rch & Prof#=BarnetRn,Main      ,1
Up Type=0
Dn Type=3
Dn Slope=0.006121

--- BarnetRn.g01 (geometry) ---

Geom Title=USGS 3m DEM
Program Version=4.00

River Reach=BarnetRn        ,Main
Reach XY= 30
     1756647.117      298213.856     1756300.841      297941.687
     1755689.199      297607.721     1755373.969      297397.745
     1754631.353      296791.935      1754414.04      296655.796
     1753927.113      296435.365     1753851.717      296420.779
      1753769.94      296517.346     1753710.402      296520.995
     1753358.392      296448.175     1752043.411      296305.581
     1751905.687      296267.762     1751737.874      296425.749
     1751079.917      296408.155     1751006.303      296357.852
     1750987.237      296250.729     1750902.586       296268.94
     1750853.953      296201.395     1750728.295      296220.534
     1750683.925      296190.438     1750661.633      296111.397
     1750587.645      296133.343     1750491.777      296248.217
     1750347.638      296234.305     1750301.748      296147.214
     1750237.163      296139.392     1750133.414       296049.58
     1749902.254      295721.515     1748986.559      295403.039

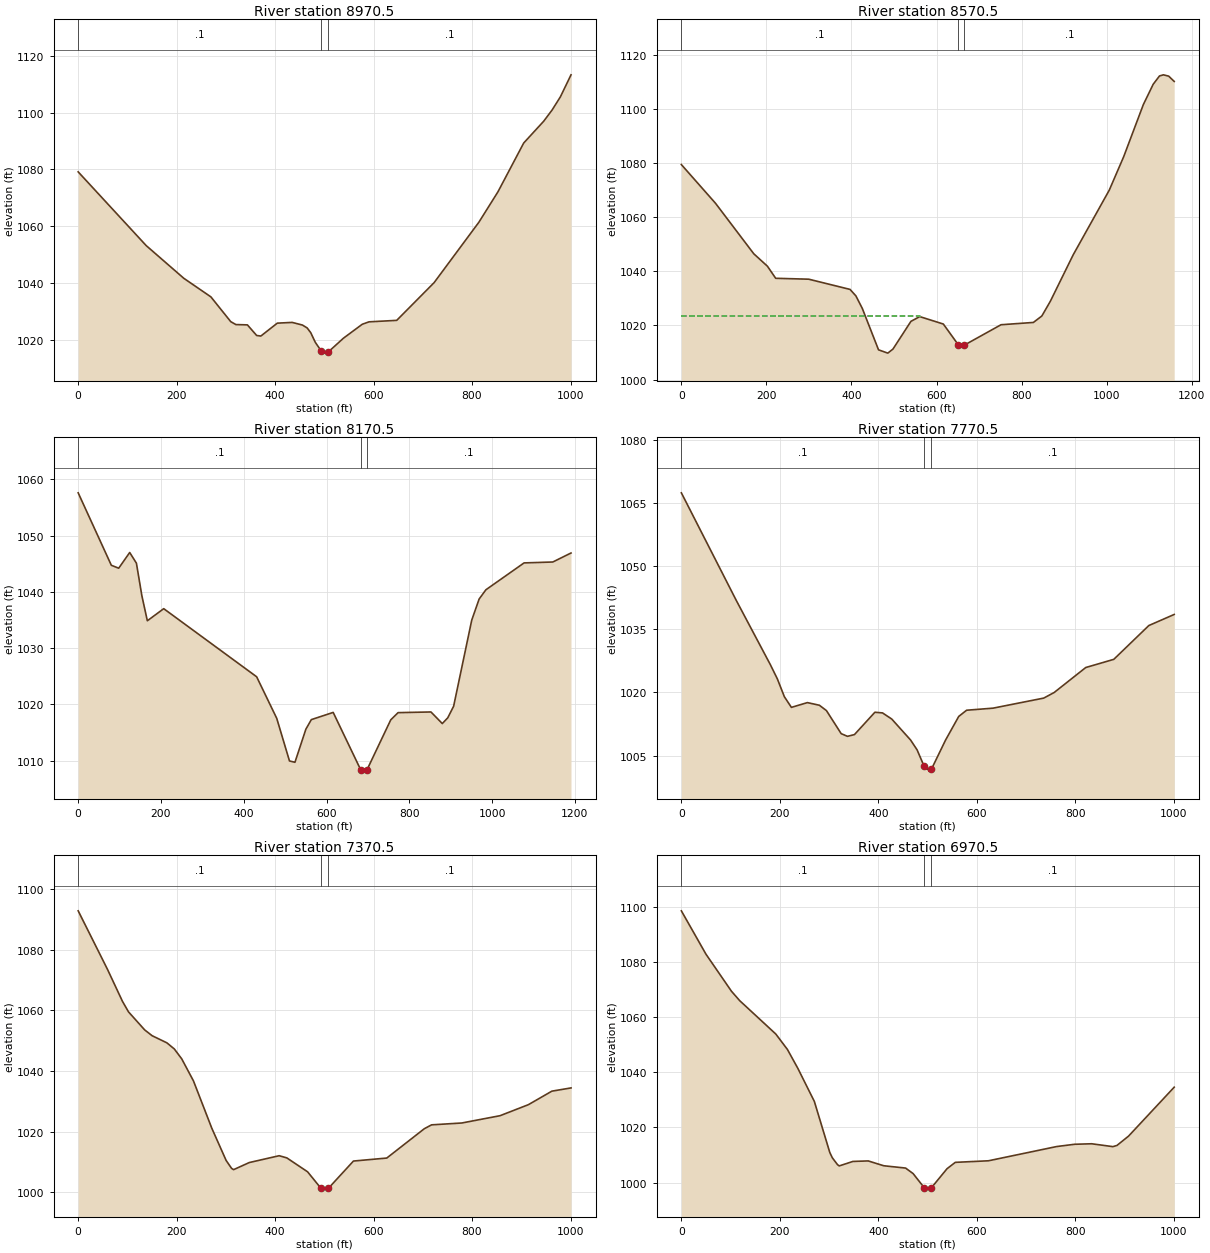
Type RM Length L Ch R = 1 ,8970.5  ,400.307,400,399.288
XS GIS Cut Line= 3
     1756950.693      297815.809     1756639.289      298207.634
     1756327.884       298599.46
#Sta/Elev= 30
       0 1079.12   138.1 1053.18   214.5 1041.67   269.6 1035.12   309.9  1026.4
   320.3 1025.38   343.7 1025.27   362.5 1021.54     371 1021.34   404.4 1025.88
   434.7 1026.14   455.5 1025.21   465.1 1024.19   472.4 1022.51   481.6 1019.14
     493 1016.25   497.7 1015.33     508 1015.75   538.9  1020.6     577 1025.49
   590.7 1026.34     647 1026.86   722.9 1040.13   813.9  1061.4   852.6  1072.1
   904.9 1089.27   945.6 1096.96   962.5 1100.87   979.4 1105.52    1001 1113.27
#Mann= 3 , 0 , 0
       0      .1       0     493    .045       0     508      .1       0
Bank Sta=493,508
XS Rating Curve= 0 ,0
Exp/Cntr=0.3,0.1

Type RM Length L Ch R = 1 ,8570.5  ,404.608,400,395.667
XS GIS Cut Line= 3
     1756727.309      297439.595     1756324.868      297960.378
     1756025.941      298361.976
#Sta/Elev= 30
       0 1079.36    80.3 1065.07   170.3 1046.42   202.4 1041.83   221.8 1037.37
   299.5 1037.04   396.6 1033.27   410.4 1030.87   425.4 1026.27   463.6 1010.96
   485.4 1009.74   497.5 1011.23   539.8 1021.47   560.5 1023.23     616 1020.48
   650.7 1012.92   665.7 1012.72   751.6 1020.22   827.7 1021.07   847.6 1023.45
   867.5 1028.86   921.3 1046.03  1006.2 1069.94  1040.1 1082.29  1086.2 1101.49
  1109.4 1109.01  1124.2 1112.08  1133.5  1112.5  1145.9 1112.01  1158.8 1110.07
#Mann= 3 , 0 , 0
       0      .1       0   650.7    .045       0   665.7      .1       0
#XS Ineff= 2 , 0
          560.14  1023.3
Permanent Ineff=
       F       F
Bank Sta=650.7,665.7
XS Rating Curve= 0 ,0
Exp/Cntr=0.3,0.1

Type RM Length L Ch R = 1 ,8170.5  ,397.049,400,403.082
XS GIS Cut Line= 3
     1756275.489      297151.083     1755973.191      297771.574
     1755756.612      298222.781
#Sta/Elev= 30
       0 1057.59    80.1 1044.72    97.9  1044.2   124.5 1046.99   140.7 1045.09
   153.9  1039.3   167.1 1034.86   206.7 1037.01   431.2 1024.91   479.7 1017.53
   510.5 1009.96   523.7 1009.72   550.1  1015.6   563.3  1017.3   616.1 1018.58
   682.7 1008.37   695.4 1008.15   697.7 1008.37   755.2 1017.26   772.9 1018.54
   852.3 1018.66   879.7  1016.6   892.9 1017.62   907.1 1019.68   950.9 1034.99
   968.7 1038.72   985.1 1040.37  1077.3 1045.14  1146.7  1045.3  1190.7  1046.9
#Mann= 3 , 0 , 0
       0      .1       0   682.7    .045       0   697.7      .1       0
#XS Ineff= 2 , 0
          616.47  1018.5
Permanent Ineff=
       F       F
Bank Sta=682.7,697.7
XS Rating Curve= 0 ,0
Exp/Cntr=0.3,0.1

Type RM Length L Ch R = 1 ,7770.5  ,398.285,400,401.715
XS GIS Cut Line= 3
     1755905.237      297150.532     1755629.096       297567.96
     1755352.954      297985.389
#Sta/Elev= 30
       0 1067.41   111.5 1041.87   180.8  1026.6     195 1023.23   209.3 1018.98
   223.5 1016.47     256  1017.6   280.4 1016.97   294.7  1015.7   324.6 1010.23
   337.4 1009.59   351.6 1010.01   393.1 1015.31   408.6 1015.15   427.4 1013.69
   465.5 1008.73   478.8 1006.38     493 1002.52   504.5 1001.33     508  1001.8
   536.7 1008.72   563.4 1014.32   579.4 1015.79     633 1016.28     736 1018.67
   757.1 1019.99   821.4 1025.93   878.3 1027.87   949.5  1035.9    1001 1038.53
#Mann= 3 , 0 , 0
       0      .1       0     493    .045       0     508      .1       0
Bank Sta=493,508
XS Rating Curve= 0 ,0
Exp/Cntr=0.3,0.1

Type RM Length L Ch R = 1 ,7370.5  ,398.908,400,401.092
XS GIS Cut Line= 3
     1755607.413      296945.297     1755300.298      297340.494
     1754993.183      297735.691
#Sta/Elev= 30
       0 1092.85    59.9 1073.42      90 1062.98   102.2 1059.53   135.1 1053.57
   150.2 1051.66   180.2 1049.31   195.3 1047.28   210.3 1044.03   234.1 1036.77
   271.5 1021.11   300.5 1010.52   311.5 1007.92   315.6 1007.48   347.6 1009.83
   408.2 1012.08   423.8 1011.36   465.9 1006.78     493 1001.36     496 1001.06
     508 1001.29   559.1 1010.32   626.8 1011.31     703 1020.98   717.8 1022.26
   779.1 1022.87   856.9 1025.28   914.5 1028.92   962.1 1033.37    1001 1034.44
#Mann= 3 , 0 , 0
       0      .1       0     493    .045       0     508      .1       0
Bank Sta=493,508
XS Rating Curve= 0 ,0
Exp/Cntr=0.3,0.1

Type RM Length L Ch R = 1 ,6970.5  ,401.244,400,398.756
XS GIS Cut Line= 3
     1755319.119      296704.479     1754993.197      297084.315
     1754667.275      297464.151
#Sta/Elev= 30
       0 1098.58      50 1082.85   101.8 1069.41   118.6 1065.98   191.9 1053.88
   215.4 1048.31   236.5 1041.48   270.1 1029.46   301.5 1010.93   306.6 1009.02
   317.1 1006.53   320.7 1006.06   348.4 1007.68   379.5 1007.87     411 1006.12
   455.4 1005.28   470.7 1003.28     493  998.23   497.5  997.64     508  998.17
   539.6 1005.04   556.4 1007.35   623.8 1007.92   762.4 1013.09   798.9 1013.91
   833.4 1014.09   876.4 1013.05   884.8 1013.49   908.3 1016.87    1001 1034.61
#Mann= 3 , 0 , 0
       0      .1       0     493    .045       0     508      .1       0
Bank Sta=493,508
XS Rating Curve= 0 ,0
Exp/Cntr=0.3,0.1

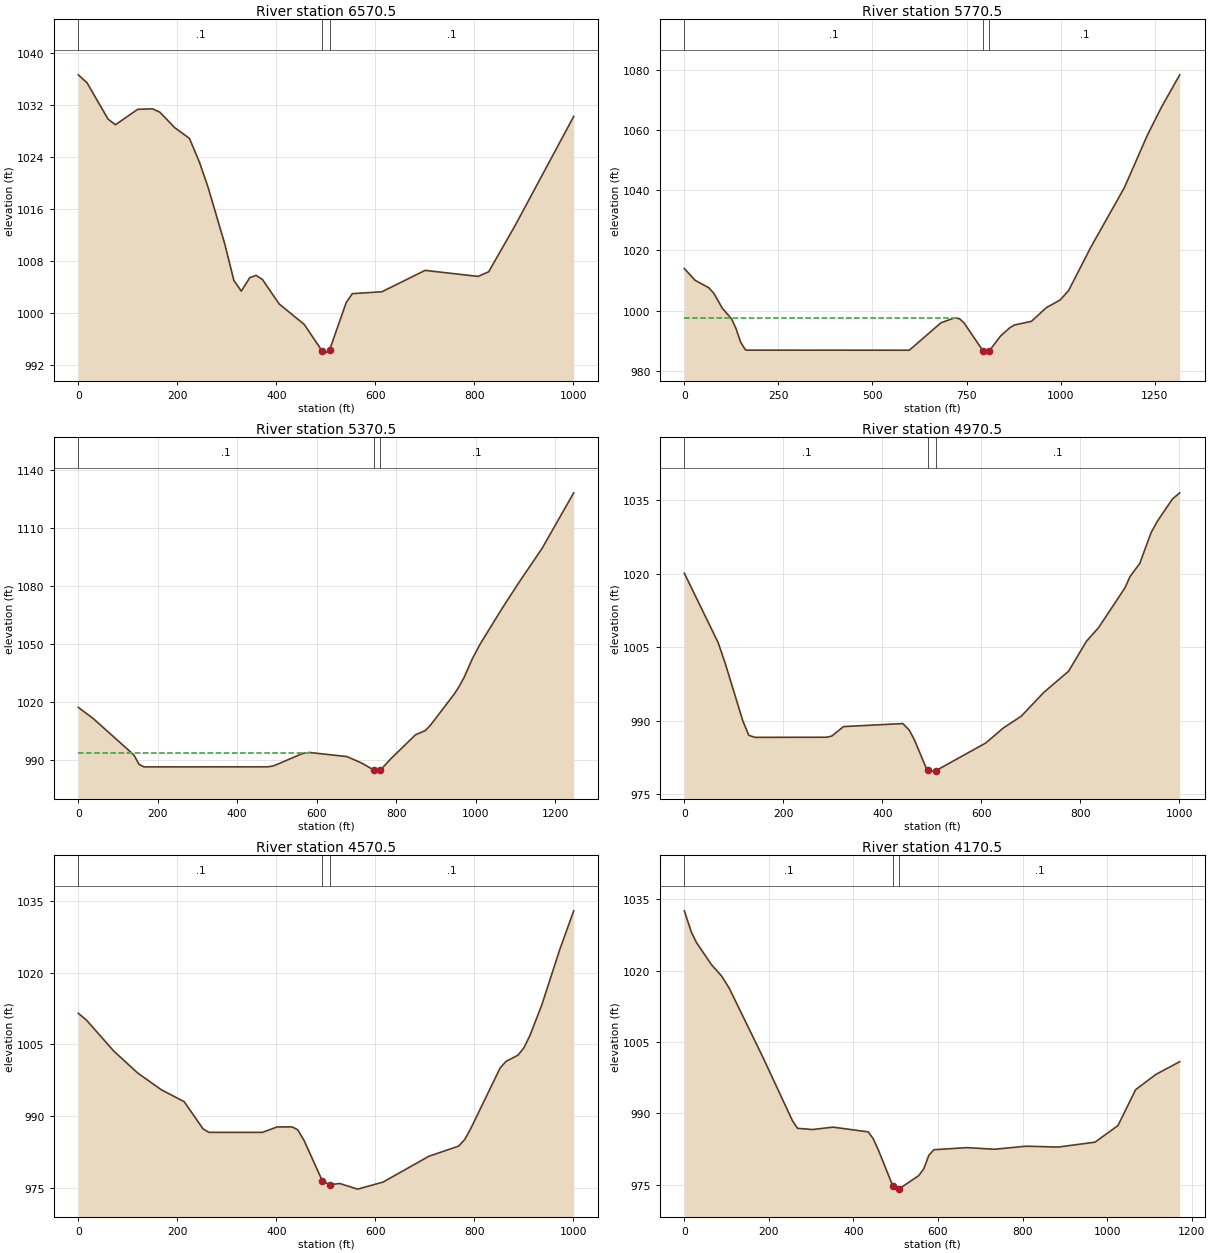
Type RM Length L Ch R = 1 ,6570.5  ,810.272,800,790.351
XS GIS Cut Line= 3
     1754987.691      296434.446      1754683.25      296831.706
     1754378.808      297228.967
#Sta/Elev= 30
       0 1036.69    17.6 1035.47      60 1029.89      75 1029.01   119.9 1031.38
   149.8 1031.46   164.7 1030.95   194.7 1028.57   224.6 1026.91   244.9 1023.22
   261.8 1019.49   295.7 1010.74   314.3 1005.07   329.3 1003.42   346.5 1005.49
   359.2 1005.84   371.9 1005.22   405.8 1001.45   456.6  998.29     493  994.17
   498.9  993.88     508  994.43   541.3 1001.66   553.7 1003.03   613.5 1003.32
   700.7 1006.61   807.9 1005.68   829.2  1006.4   882.7 1013.52    1001 1030.29
#Mann= 3 , 0 , 0
       0      .1       0     493    .045       0     508      .1       0
Bank Sta=493,508
XS Rating Curve= 0 ,0
Exp/Cntr=0.3,0.1

Type RM Length L Ch R = 1 ,5770.5  ,398.277,400,399.047
XS GIS Cut Line= 3
     1754138.867      295670.417      1753979.51      296456.952
     1753863.964      296957.834
#Sta/Elev= 30
       0 1013.95    28.7 1010.04      65 1007.58    78.3 1005.73   101.3 1000.71
   125.6  997.22   137.7  993.91   149.8  989.46   161.9     987   166.5  986.83
     598  986.81     682  995.92   719.1   997.6   731.3  997.28   743.1  995.94
     795  986.39   803.5  985.84     810  986.51   840.5  991.54   864.9  994.26
   877.1  995.18   922.3  996.39   961.9 1000.94   998.9 1003.51  1021.3 1006.65
  1080.7 1021.13  1169.5 1040.84  1230.4 1058.21  1268.9 1067.76  1316.6 1078.32
#Mann= 3 , 0 , 0
       0      .1       0     795    .045       0     810      .1       0
#XS Ineff= 2 , 0
          724.18  997.64
Permanent Ineff=
       F       F
Bank Sta=795,810
XS Rating Curve= 0 ,0
Exp/Cntr=0.3,0.1

Type RM Length L Ch R = 1 ,5370.5  ,404.075,400,397.261
XS GIS Cut Line= 3
      1753858.52      295790.177     1753631.455      296506.793
     1753510.085      296986.984
#Sta/Elev= 30
       0 1017.32    38.5 1011.37     128  994.95   140.5  992.55   152.9   987.9
   165.4   986.6   476.7  986.64   489.2  987.03   501.6  987.98   563.9   993.5
   581.5  994.05     676  991.93   713.4  988.58   744.2  984.92   750.7  984.42
   759.2   985.1     763  985.52   786.8  990.83   848.7 1003.16   873.2 1005.31
   885.5 1007.87   946.7 1024.29   958.9 1028.19   971.2 1032.82   992.1 1042.52
  1011.6    1050  1067.2  1068.5  1109.4 1081.82  1167.1 1099.24    1247 1127.97
#Mann= 3 , 0 , 0
       0      .1       0   744.2    .045       0   759.2      .1       0
#XS Ineff= 2 , 0
          584.06  994.01
Permanent Ineff=
       F       F
Bank Sta=744.2,759.2
XS Rating Curve= 0 ,0
Exp/Cntr=0.3,0.1

Type RM Length L Ch R = 1 ,4970.5  ,399.412,400,400.588
XS GIS Cut Line= 3
      1753301.72      295937.279     1753238.865      296433.817
     1753176.011      296930.354
#Sta/Elev= 30
       0 1020.12    68.4 1005.93    82.4 1001.79   118.3  989.94   130.3  987.02
   142.3   986.6   287.6  986.62   297.9  986.86   321.8   988.8   441.5  989.41
   454.5  988.08   465.1  986.04   489.3  980.19     493  980.02   500.5   979.7
     508  979.78     609  985.44   644.9  988.53   680.8  990.92   726.1  995.75
   776.5 1000.11   812.5 1006.22   836.9 1008.98   890.5 1017.15   900.6 1019.44
   920.2  1022.1   943.1 1028.39   956.1 1030.78   986.4 1035.28    1001 1036.53
#Mann= 3 , 0 , 0
       0      .1       0     493    .045       0     508      .1       0
Bank Sta=493,508
XS Rating Curve= 0 ,0
Exp/Cntr=0.3,0.1

Type RM Length L Ch R = 1 ,4570.5  ,400.916,400,398.76
XS GIS Cut Line= 3
     1752917.948      295888.719     1752842.137      296383.444
     1752766.327       296878.17
#Sta/Elev= 30
       0  1011.5    16.2 1010.11    71.8 1003.59   119.9  999.03   167.9  995.51
     214  993.02     252  987.34     264  986.61   372.1  986.61   401.5  987.74
   432.1  987.75   443.2  987.15   456.2  984.92     493  976.48     508  975.66
   528.2  975.92   564.3  974.74   615.7  976.21   708.4  981.61   768.5  983.74
   780.5  985.08   792.5   987.3   852.5 1000.11   864.6 1001.48   888.6 1002.76
   900.6 1004.34   912.6 1006.87   936.6 1013.28   972.7  1024.8    1001 1032.93
#Mann= 3 , 0 , 0
       0      .1       0     493    .045       0     508      .1       0
Bank Sta=493,508
XS Rating Curve= 0 ,0
Exp/Cntr=0.3,0.1

Type RM Length L Ch R = 1 ,4170.5  ,399.355,400,399.605
XS GIS Cut Line= 3
     1752501.536      295836.014     1752445.763      296333.397
     1752380.577      297001.383
#Sta/Elev= 30
       0  1032.6    16.9 1028.08    28.9  1025.9    64.7 1021.22    88.6 1018.85
   106.5 1016.27   184.2 1002.11   255.9  988.42   267.8  986.85   303.7   986.6
   351.5   987.1   435.1   986.1     447  984.63     459  982.28     493  974.76
   506.8  974.06     508  974.12   554.5  976.91   566.4  978.35   578.3  981.17
   590.3  982.35   668.7  982.79   733.4  982.45   808.4  983.09   884.4  982.91
   971.4  983.94  1025.6  987.43  1067.4  994.98  1115.1  998.18  1171.7 1000.87
#Mann= 3 , 0 , 0
       0      .1       0     493    .045       0     508      .1       0
Bank Sta=493,508
XS Rating Curve= 0 ,0
Exp/Cntr=0.3,0.1

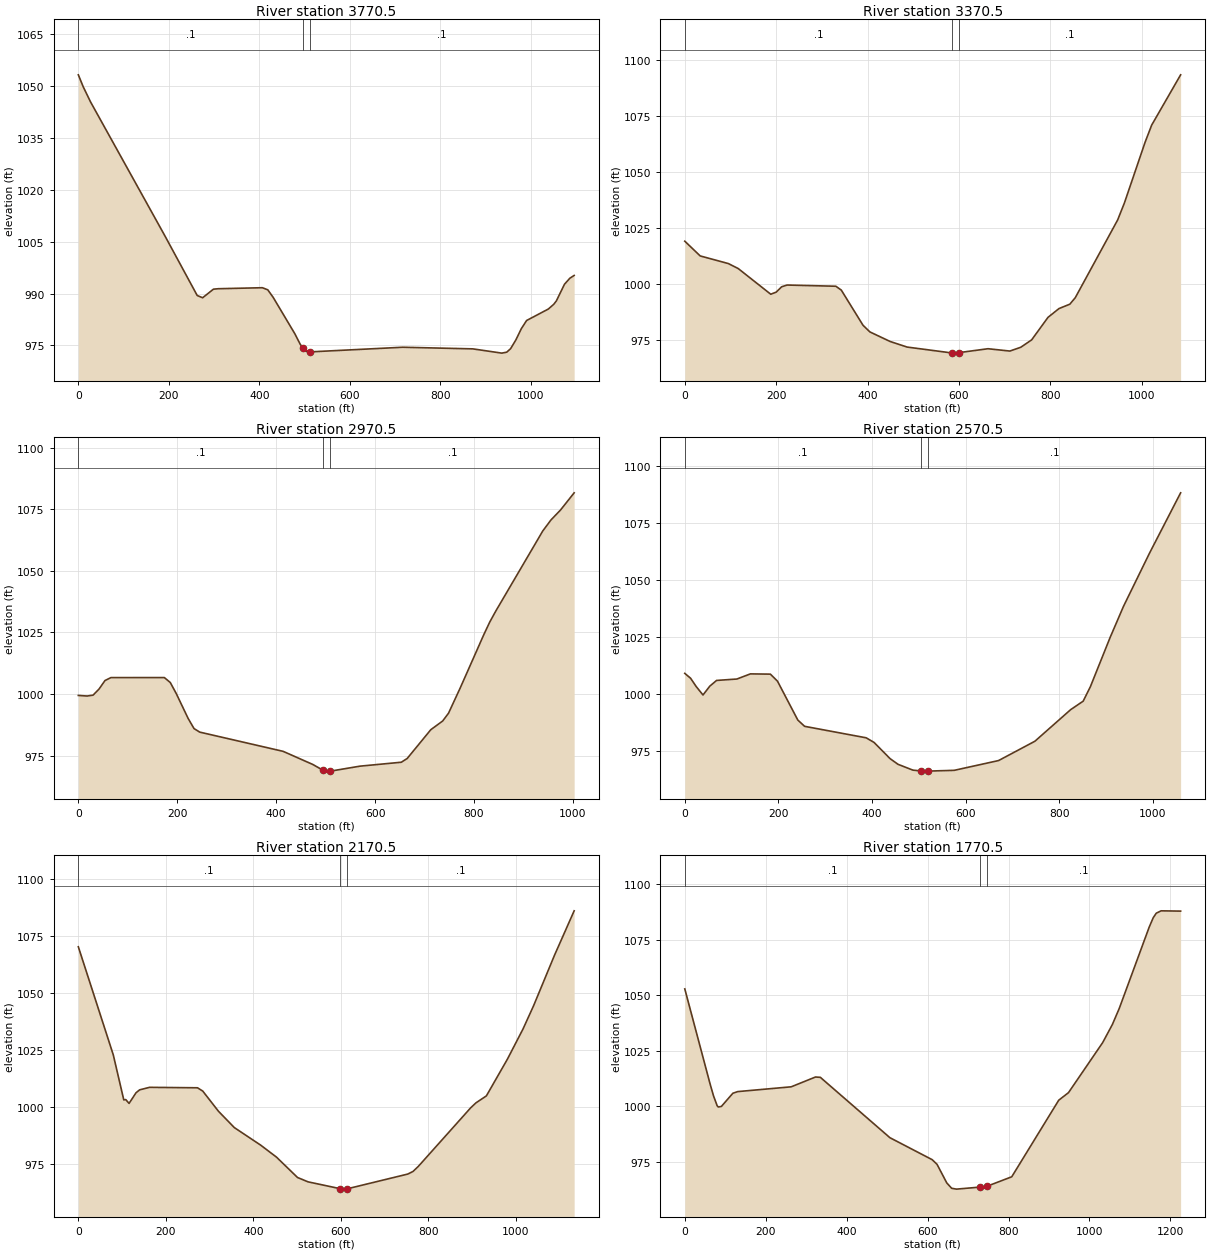
Type RM Length L Ch R = 1 ,3770.5  ,403.557,400,400.659
XS GIS Cut Line= 3
     1752123.713      295806.556     1752050.144      296306.098
     1751999.523      296895.232
#Sta/Elev= 30
       0  1053.2    10.8 1049.75    26.9  1045.4   190.8 1006.81   262.8  989.44
   274.8  988.78   298.7  991.26   309.4  991.39   406.8  991.68   418.8  991.08
   430.8  988.89   478.8  978.35   490.8  975.28   497.4  974.23   502.8  973.31
   512.4  973.14   717.3  974.48   872.2  974.01   936.2  972.78   947.2  973.06
   955.7  974.07   967.6  976.66   979.5  979.87   991.1  982.21  1039.1  985.52
    1051  986.88  1056.9  987.88  1074.8  992.68  1086.7  994.43  1096.2  995.23
#Mann= 3 , 0 , 0
       0      .1       0   497.4    .045       0   512.4      .1       0
Bank Sta=497.4,512.4
XS Rating Curve= 0 ,0
Exp/Cntr=0.3,0.1

Type RM Length L Ch R = 1 ,3370.5  ,395.233,400,400.001
XS GIS Cut Line= 3
     1751735.507      295831.004      1751723.24      296423.696
     1751670.782      296913.038
#Sta/Elev= 30
       0 1019.13    33.7 1012.57    95.3 1009.17   116.9 1006.95   188.1  995.51
     200  996.45   211.9  998.82   223.7   999.6   330.6  999.07   342.5  997.34
     390  981.69   405.1  978.72   449.4  974.46   486.5  971.98   585.3  969.33
   591.9  969.28   600.3  969.51   663.5  971.24   711.3   970.2   735.1  971.88
     759  975.18   794.8  985.21   818.7  989.11   842.6  991.08   854.5  993.98
   947.2 1028.59     962 1036.17  1007.1 1063.12  1021.7 1070.85    1085 1093.23
#Mann= 3 , 0 , 0
       0      .1       0   585.3    .045       0   600.3      .1       0
Bank Sta=585.3,600.3
XS Rating Curve= 0 ,0
Exp/Cntr=0.3,0.1

Type RM Length L Ch R = 1 ,2970.5  ,396.698,400,387.775
XS GIS Cut Line= 3
     1751403.551      295906.437     1751329.247       296403.08
     1751284.848      296901.285
#Sta/Elev= 30
       0  999.45    17.8  999.21    29.8  999.57    41.9 1002.05    53.9  1005.5
    65.9 1006.69   173.9  1006.7   185.9 1004.69   197.9 1000.24   221.9  990.15
   233.9     986   245.5  984.56     414  976.76     474  971.44   494.7  969.09
   509.7  968.73   569.6  970.75     653  972.34   664.9  973.87   712.6  985.55
   736.6  989.08   748.4  992.23   772.2 1002.55   819.9 1024.19   831.8 1029.25
   843.7  1033.6   939.1 1066.25   955.4 1070.64   974.9 1074.72  1002.4 1081.68
#Mann= 3 , 0 , 0
       0      .1       0   494.7    .045       0   509.7      .1       0
Bank Sta=494.7,509.7
XS Rating Curve= 0 ,0
Exp/Cntr=0.3,0.1

Type RM Length L Ch R = 1 ,2570.5  ,404.422,400,412.088
XS GIS Cut Line= 3
     1751305.488      295880.284     1751012.428      296300.704
     1750721.632       296764.17
#Sta/Elev= 30
       0 1008.94    12.4  1006.8    24.4 1003.15    38.9  999.45    53.4 1003.32
    67.9 1005.84   111.3 1006.46   140.2 1008.72   182.9 1008.61   198.1 1005.51
   241.5  988.44     256  985.68   387.6  980.63   404.6  978.58   438.7  971.48
   455.8  968.97   487.6  966.42     505  966.06   514.2  965.99     520     966
   575.8  966.34   670.5  970.63   748.1  979.11   824.7  993.02   851.4  996.74
   866.8 1003.12   908.8 1024.65   937.5 1038.39   992.9 1061.68  1059.6 1088.28
#Mann= 3 , 0 , 0
       0      .1       0     505    .045       0     520      .1       0
Bank Sta=505,520
XS Rating Curve= 0 ,0
Exp/Cntr=0.3,0.1

Type RM Length L Ch R = 1 ,2170.5  ,400.694,400,396.308
XS GIS Cut Line= 3
     1750799.204      295607.816     1750700.788      296205.613
     1750631.278      296728.426
#Sta/Elev= 30
       0 1070.09    79.9 1022.71   103.9 1002.98   108.3 1003.12     116 1001.44
   131.8 1006.08     140 1007.37   162.8 1008.48   272.4 1008.28   284.4 1006.84
   320.5  997.95   356.6  990.83   416.8  983.14   452.9  977.89     501  968.96
   525.1  967.05   598.3  964.06   609.3  963.86   613.3  963.94     753  970.46
     765  971.61     777   973.8   896.7  999.48   908.7 1001.65   932.7 1004.74
   980.6 1020.78  1016.5 1034.09  1040.4 1044.17  1088.4 1066.39  1133.3 1085.85
#Mann= 3 , 0 , 0
       0      .1       0   598.3    .045       0   613.3      .1       0
Bank Sta=598.3,613.3
XS Rating Curve= 0 ,0
Exp/Cntr=0.3,0.1

Type RM Length L Ch R = 1 ,1770.5  ,389.372,400,416.919
XS GIS Cut Line= 3
     1750546.076       295509.83     1750433.879      296239.329
     1750351.719      296719.615
#Sta/Elev= 30
       0 1052.83    62.2 1010.26    70.8 1004.79      80 1000.23    82.8  999.68
    90.4  999.92   118.8 1005.86   130.8  1006.6     263 1008.76     323 1013.17
     335 1013.02   506.9  985.85   611.3  975.96   623.3  973.88   647.4   965.5
   659.4  963.09   671.4   962.7   730.6  963.63   745.6   963.9     808  968.26
   924.1 1002.73   948.2 1006.13  1032.6 1028.64  1056.6 1036.79  1073.8 1044.11
  1147.4 1080.53  1157.7 1084.91  1165.1 1086.91  1177.1 1087.98  1225.3 1087.85
#Mann= 3 , 0 , 0
       0      .1       0   730.6    .045       0   745.6      .1       0
Bank Sta=730.6,745.6
XS Rating Curve= 0 ,0
Exp/Cntr=0.3,0.1

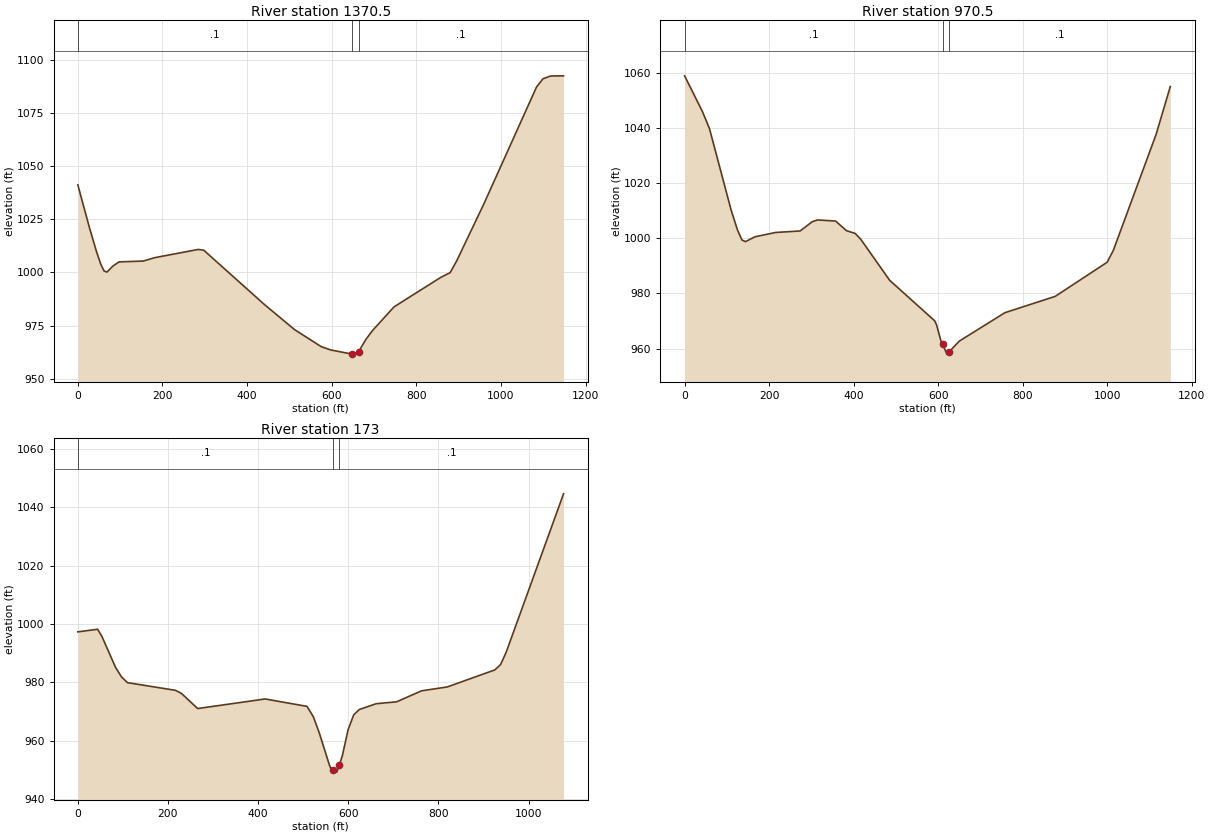
Type RM Length L Ch R = 1 ,1370.5  ,399.302,400,394.369
XS GIS Cut Line= 3
     1750494.361      295498.943     1750128.568      296043.517
     1749751.343      296359.393
#Sta/Elev= 30
       0 1041.21    27.8 1020.83    44.9 1009.32    54.5 1003.76      62 1000.69
    68.8 1000.18    83.1 1003.03    97.4 1004.97   154.6 1005.35   181.8 1006.95
   284.5 1010.82   297.6 1010.47   440.6  984.98   512.1  973.12   575.4  965.07
     598  963.52   648.5  961.58   655.2  961.57   663.5  962.73   681.2  968.59
   696.7  972.71   747.4  983.81   858.3  997.73   879.9  999.89   895.3 1005.37
     960 1032.37  1083.9 1087.13  1099.3  1091.1  1117.2 1092.41    1148  1092.5
#Mann= 3 , 0 , 0
       0      .1       0   648.5    .045       0   663.5      .1       0
Bank Sta=648.5,663.5
XS Rating Curve= 0 ,0
Exp/Cntr=0.3,0.1

Type RM Length L Ch R = 1 ,970.5   ,801.411,797.519,790.947
XS GIS Cut Line= 3
      1750252.12      295213.153     1749898.267      295720.069
     1749589.932      296152.523
#Sta/Elev= 30
       0 1058.81    42.3 1045.85      59 1039.64   110.1 1010.21   125.2 1002.95
   135.7  999.35   144.2  998.74   166.7  1000.5   215.4 1002.06   273.4 1002.61
   302.3 1005.98   314.8  1006.6   357.4  1006.2     383 1002.71   403.7 1001.72
   417.1  999.56   485.3  984.72   591.9  970.05   596.2  968.62   606.4  962.88
   610.7  961.49   620.9  957.99   625.7  958.77     650   962.7   757.9     973
   877.1  978.92    1000  991.29  1014.6  995.61  1115.5 1037.49  1149.3 1054.92
#Mann= 3 , 0 , 0
       0      .1       0   610.7    .045       0   625.7      .1       0
Bank Sta=610.7,625.7
XS Rating Curve= 0 ,0
Exp/Cntr=0.3,0.1

Type RM Length L Ch R = 1 ,173     ,175.268,172.975,173.12
XS GIS Cut Line= 3
     1749405.637      294946.869     1749151.601      295454.941
     1748988.293      295937.608
#Sta/Elev= 30
       0   997.3    43.9  998.19    53.5  995.72    83.7  985.12      97  981.84
   110.3  979.88   216.5  977.26   229.7  976.22   265.9  971.01   415.6  974.29
   508.5  971.75   522.5   968.2   535.1  962.93   557.9  951.78   561.6  950.38
   565.4  950.09   574.5  949.21   580.4  951.77     587  954.92   599.6  963.75
   612.1  968.86   624.6  970.69   662.2  972.67   707.2  973.31   762.5  977.08
   819.6  978.41   925.4  984.27     938  986.11   950.2  990.25  1077.6 1044.62
#Mann= 3 , 0 , 0
       0      .1       0   565.4    .045       0   580.4      .1       0
Bank Sta=565.4,580.4
XS Rating Curve= 0 ,0
Exp/Cntr=0.3,0.1

Chan Stop Cuts=-1
Use User Specified Reach Order=0